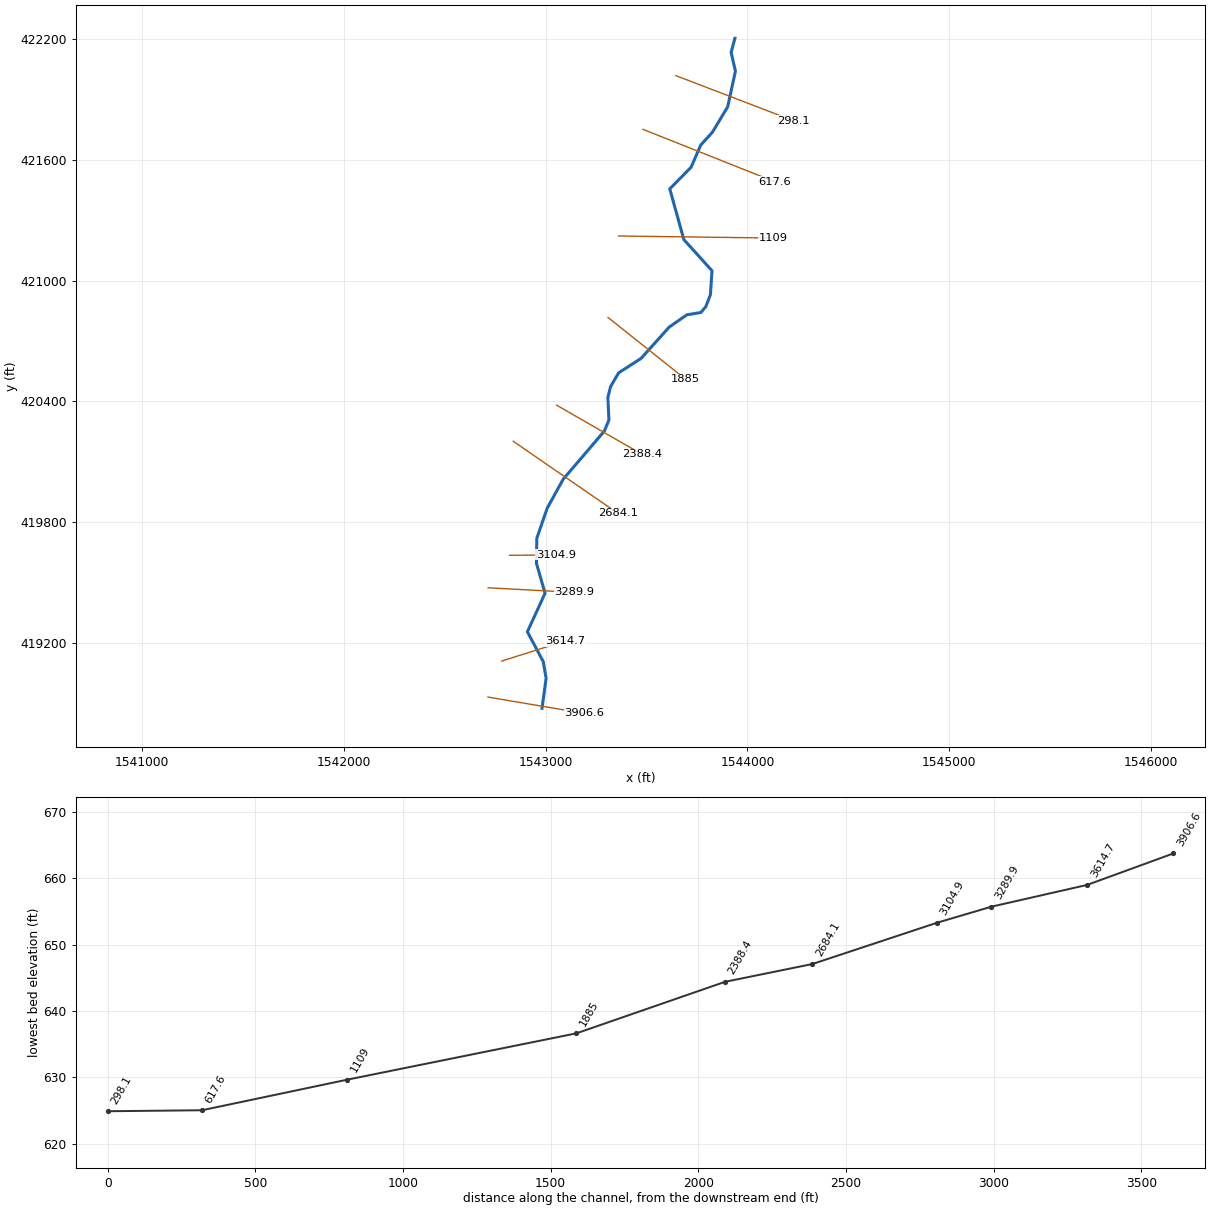
--- JOELSBR.prj (project) ---

Proj Title=JOELSBR
Current Plan=p01
Default Exp/Contr=0,0
English Units
Geom File=g01
Flow File=f01
Plan File=p01
BEGIN DESCRIPTION:
END DESCRIPTION:
DSS Export Rating Curves= 0
DSS Export Rating Curve Sorted= 0
DSS Export Volume Flow Curves= 0
DXF OffsetX= 0
DXF OffsetY= 0
DXF ScaleX= 0
DXF ScaleY= 0

--- JOELSBR.p01 (plan) ---

Plan Title=Floodplain
Program Version=4.00
Geom File=g01
Flow File=f01
K Sum by GR=0
Std Step Tol=0.01
Critical Tol=0.01
Num of Std Step Trials=20
Max Error Tol=0.3
Flow Tol Ratio=0.001
Split Flow NTrial=30
Split Flow Tol=0.02
Split Flow Ratio=0.02
Log Output Level=0
Friction Slope Method=1
Unsteady Friction Slope Method=2
Unsteady Bridges Friction Slope Method=1
Global Log Level=0
CheckData=False
Run HTab=0
Run UNet=0
Run PostProcess=0
UNET Theta=0
UNET Theta Warmup=0
UNET ZTol=0
UNET ZSATol=0
UNET MxIter=0
UNET MaxInSteps=0
UNET DtIC=0
UNET DtMin=0
UNET MaxCRTS=0
UNET WFStab=0
UNET SFStab=0
UNET WFX=0
UNET SFX=0
UNET DSS MLevel=0
UNET DZMax Abort=0
UNET Convert EG Bridges=0
UNET Use Existing IB Tables=0
UNET Froude Limit=0
UNET Froude Power=0
Write IC File=0
Echo Input=False
Echo Output=False
Write Detailed=0

--- JOELSBR.f01 (steady flow) ---

Flow Title=NFF Regression Equation
Program Version=4.00
Number of Profiles=1
Profile Names=P100yr
River Rch & RM=JOELSBR,Main      ,3906.6
365.6120
River Rch & RM=JOELSBR,Main      ,3289.9
417.2420
River Rch & RM=JOELSBR,Main      ,2684.1
422.2860
River Rch & RM=JOELSBR,Main      ,2388.4
493.3640
River Rch & RM=JOELSBR,Main      ,298.1
524.1259
Boundary for River Rch & Prof#=JOELSBR,Main      ,1
Up Type=0
Dn Type=3
Dn Slope=0.006275

--- JOELSBR.g01 (geometry) ---

Geom Title=Geometry
Program Version=4.00

River Reach=JOELSBR         ,Main
Reach XY= 30
     1542981.987      418876.387     1543002.259      419025.701
     1542988.143       419107.92     1542909.461      419256.372
     1542997.039      419447.654     1542954.261      419596.027
     1542956.223      419721.126     1543008.225      419871.244
     1543086.718      420013.514     1543291.087      420253.182
     1543313.413      420307.712     1543308.407      420420.066
     1543321.217      420472.699     1543361.445      420541.872
     1543473.018      420613.967     1543612.866      420769.922
     1543699.839      420830.137     1543768.777      420841.798
     1543793.386      420870.284      1543816.32       420929.81
     1543824.239      421049.186     1543684.663      421203.735
      1543615.07      421455.501     1543720.828       421563.16
     1543768.283      421672.907     1543826.044      421736.641
     1543901.769      421862.728     1543940.333      422040.113
     1543919.007      422133.646      1543937.71       422203.07

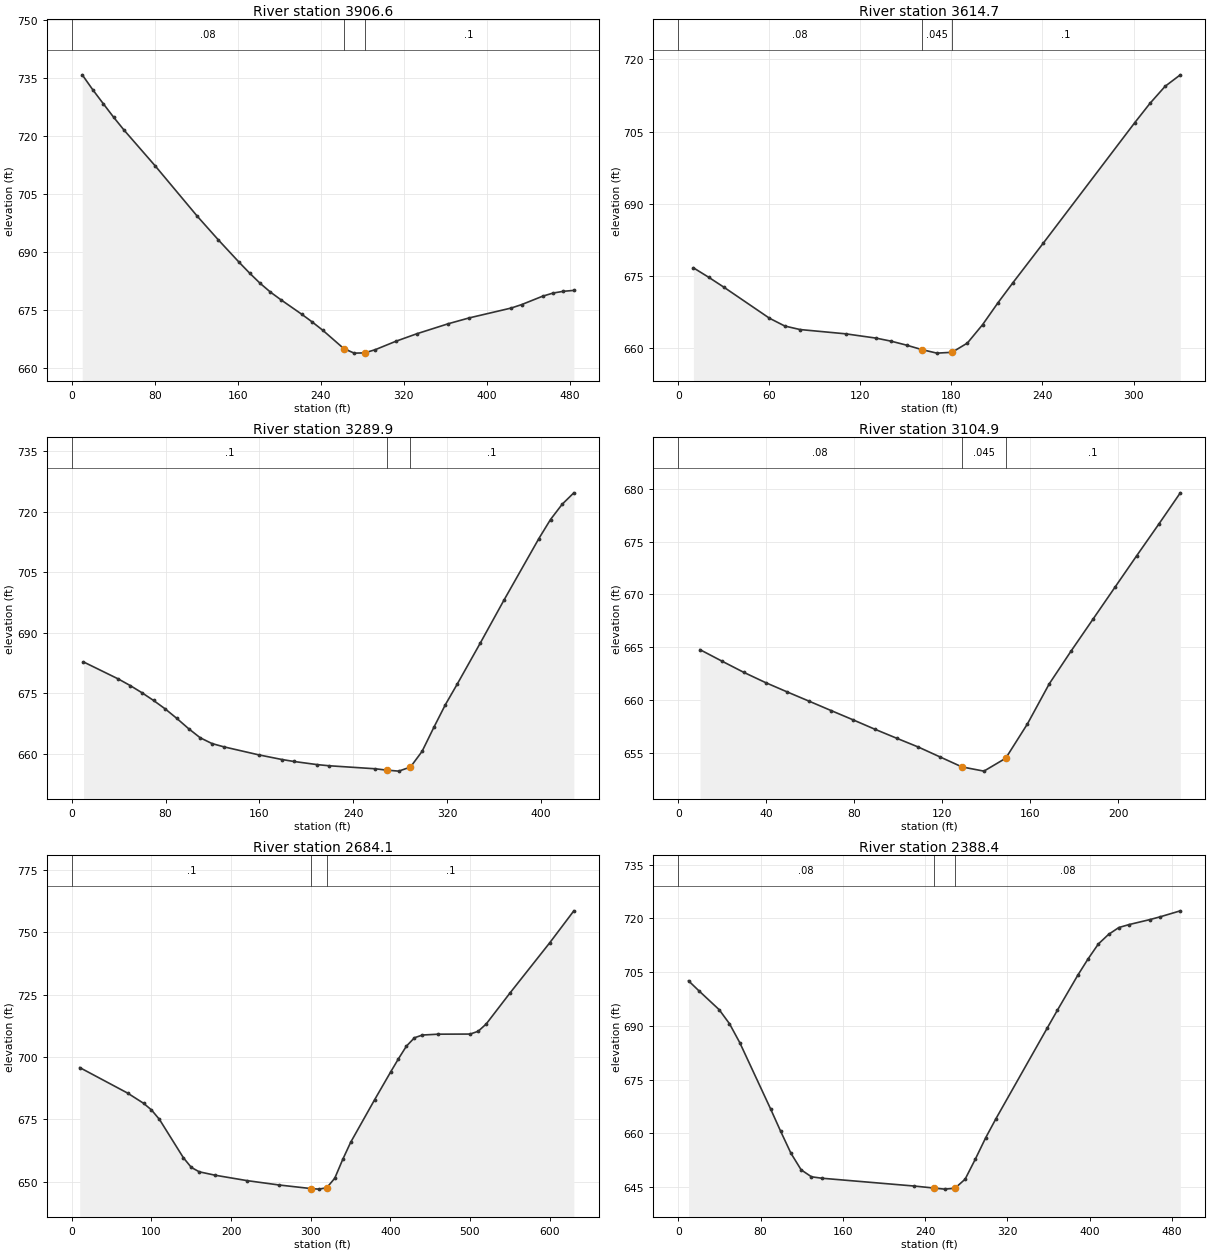
Type RM Length L Ch R = 1 ,3906.6  ,279.9,291.8,303.7
XS GIS Cut Line= 2
     1542714.229         418932.     1543191.564      418851.061
#Sta/Elev= 30
    10.1  735.73    20.2  731.89    30.3  728.29    40.3  724.78    50.4  721.43
    80.7  712.09     121  699.15   141.2  693.06   161.4  687.22   171.5  684.42
   181.6  681.79   191.6   679.5   201.7  677.52   221.9  673.75     232  671.75
   242.1  669.62   262.3  664.89   272.3  663.72   282.3  663.78   292.5   664.6
   312.7  666.81   332.9  668.75   363.1  671.33   383.3  672.84   423.6  675.38
   433.7  676.27   453.9  678.44     464  679.26   474.1  679.72   484.1  679.95
#Mann= 3 , 0 , 0
       0     .08       0   262.3    .045       0   282.3      .1       0
Bank Sta=262.3,282.3
XS Rating Curve= 0 ,0
Exp/Cntr=0.3,0.1

Type RM Length L Ch R = 1 ,3614.7  ,333.8,324.8,315.8
XS GIS Cut Line= 2
     1542781.767      419110.785     1543097.223      419210.403
#Sta/Elev= 22
      10   676.7      20  674.75    30.1  672.67    60.1  666.23    70.2  664.61
    80.2  663.88   110.3  662.99   130.3   662.1   140.3  661.46   150.4  660.64
   160.4  659.72   170.4  658.98   180.4  659.15   190.5  661.07   200.5  664.88
   210.5  669.37   220.5   673.6   240.6  681.86   300.7  706.81   310.8  710.85
   320.8   714.4   330.8  716.78
#Mann= 3 , 0 , 0
       0     .08       0   160.4    .045       0   180.4      .1       0
Bank Sta=160.4,180.4
XS Rating Curve= 0 ,0
Exp/Cntr=0.3,0.1

Type RM Length L Ch R = 1 ,3289.9  ,183.4,185.1,186.7
XS GIS Cut Line= 2
     1542714.406      419474.684     1543141.932      419451.855
#Sta/Elev= 30
      10  682.75    39.8  678.51    49.8   676.9    59.7  675.14    69.7  673.21
    79.7   671.1    89.6  668.75    99.6  666.22   109.5  663.96   119.5  662.53
   129.4  661.73   159.3  659.73   179.2  658.57   189.2  658.09   209.1  657.31
     219  657.03   258.9  656.27   268.8  655.93   278.8  655.69   288.8  656.71
   298.7  660.59   308.7  666.52   318.6  672.18   328.6  677.22   348.5  687.52
   368.4     698   398.3  713.33   408.2  718.04   418.2  721.84   428.1  724.65
#Mann= 3 , 0 , 0
       0      .1       0   268.8    .045       0   288.8      .1       0
Bank Sta=268.8,288.8
XS Rating Curve= 0 ,0
Exp/Cntr=0.3,0.1

Type RM Length L Ch R = 1 ,3104.9  ,436.2,420.8,405.5
XS GIS Cut Line= 2
     1542821.199      419635.853      1543049.49      419637.929
#Sta/Elev= 24
     9.9  664.77    19.9  663.68    29.8  662.62    39.7  661.65    49.6  660.76
    59.6  659.88    69.5     659    79.4  658.13    89.3  657.24    99.3  656.38
   109.2  655.54   119.1   654.6     129  653.66     139  653.26   148.9  654.48
     149  654.51   158.8  657.74   168.7  661.53   178.7  664.66   188.6  667.66
   198.5  670.66   208.4  673.65   218.4  676.63   228.3  679.63
#Mann= 3 , 0 , 0
       0     .08       0     129    .045       0     149      .1       0
Bank Sta=129,149
XS Rating Curve= 0 ,0
Exp/Cntr=0.3,0.1

Type RM Length L Ch R = 1 ,2684.1  ,293.4,295.7,298
XS GIS Cut Line= 2
     1542839.359       420202.17     1543358.201      419844.169
#Sta/Elev= 30
      10   695.8      70  685.59    90.1  681.49   100.1  678.81   110.1  675.01
   140.1  659.67   150.1  655.77   160.1     654   180.1  652.63   220.1  650.47
   260.2  648.72   300.2  647.29   310.2  647.06   320.2  647.62   330.2  651.43
   340.2  658.96   350.2  665.85   380.2  682.88   400.2  693.94   410.2  699.34
   420.2   704.4   430.3  707.76   440.3  708.85   460.3  709.19   500.3  709.24
   510.3  710.36   520.3  713.26   550.3  725.73   600.3  745.91   630.4  758.65
#Mann= 3 , 0 , 0
       0      .1       0   300.2    .045       0   320.2      .1       0
Bank Sta=300.2,320.2
XS Rating Curve= 0 ,0
Exp/Cntr=0.3,0.1

Type RM Length L Ch R = 1 ,2388.4  ,507.3,503.4,499.5
XS GIS Cut Line= 2
     1543054.362      420381.487     1543477.218      420137.632
#Sta/Elev= 30
      10  702.59    19.9  699.85    39.8  694.52    49.8  690.61    59.8  685.32
    89.7  666.85    99.6  660.52   109.6  654.39   119.5  649.77   129.5  647.83
   139.5  647.43   229.1  645.25     249  644.67     259  644.38     269  644.62
   278.9  647.16   288.9   652.8   298.9  658.74   308.8  664.03   358.6  689.33
   368.6  694.37   388.5  704.18   398.5  708.74   408.4  712.87   418.4  715.57
   428.4  717.48   438.3   718.3   458.2  719.67   468.2  720.44   488.1  722.14
#Mann= 3 , 0 , 0
       0     .08       0     249    .045       0     269     .08       0
Bank Sta=249,269
XS Rating Curve= 0 ,0
Exp/Cntr=0.3,0.1

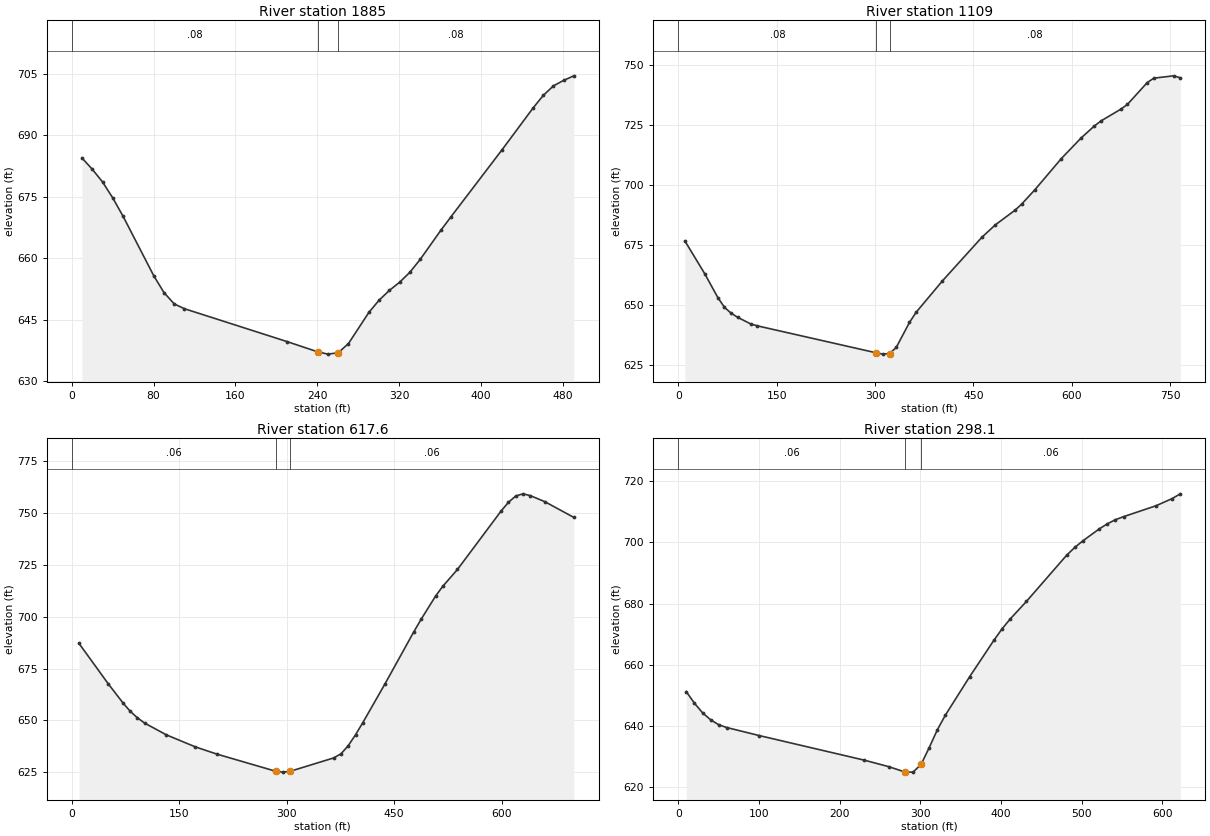
Type RM Length L Ch R = 1 ,1885    ,759.3,776,792.7
XS GIS Cut Line= 2
     1543308.911      420816.998     1543692.854      420510.881
#Sta/Elev= 28
      10  684.48      20  681.75    30.1  678.63    40.1  674.73    50.1  670.29
    80.2  655.74    90.2  651.63   100.2  648.87   110.2   647.7   210.4  639.69
   240.5  637.18   250.5  636.62   260.5  636.94   270.6   639.2   290.6  646.82
   300.6   649.8   310.7  652.19   320.7  654.18   330.7  656.61   340.7  659.72
   360.8  666.79   370.8  670.12   420.9  686.52     451  696.64     461  699.73
     471  702.07     481  703.42     491  704.53
#Mann= 3 , 0 , 0
       0     .08       0   240.5    .045       0   260.5     .08       0
Bank Sta=240.5,260.5
XS Rating Curve= 0 ,0
Exp/Cntr=0.3,0.1

Type RM Length L Ch R = 1 ,1109    ,500.1,491.3,482.5
XS GIS Cut Line= 2
     1543360.795      421221.694     1544126.087      421211.317
#Sta/Elev= 30
    10.1  676.73    40.3  663.13    60.4  653.15    70.5  649.11    80.6  646.67
    90.6  644.95   110.8  642.16   120.8  641.39   302.2  630.16   312.2  629.64
   322.2  629.87   332.3   632.4   352.5  642.81   362.5  646.99   402.8  660.12
   463.2  678.32   483.4   683.4   513.6  689.53   523.7  692.08   543.8  698.04
   584.1     711   614.3  719.58   634.4  724.53   644.5  726.63   674.7  731.52
   684.8  733.51     715  742.59   725.1  744.43   755.3  745.39   765.4  744.57
#Mann= 3 , 0 , 0
       0     .08       0   302.2    .045       0   322.2     .08       0
Bank Sta=302.2,322.2
XS Rating Curve= 0 ,0
Exp/Cntr=0.3,0.1

Type RM Length L Ch R = 1 ,617.6   ,319.3,319.6,319.8
XS GIS Cut Line= 2
     1543482.723      421750.913      1544133.87      421491.492
#Sta/Elev= 30
    10.2   687.1    50.8  667.71    71.1   658.6    81.3  654.51    91.4  651.31
   101.6  648.73   132.1  643.02   172.7  637.19   203.2  633.67   284.6  625.48
   294.6  625.04   304.6  625.41   365.7   631.9   375.9   633.9     386  637.81
   396.2  643.11   406.3  648.91   436.8  667.34   477.4  692.67   487.6  698.73
   507.9  709.99   518.1  714.78   538.4  722.81   599.3  750.99   609.5  755.18
   619.7  758.24   629.8  759.31     640  758.46   660.3  755.54   700.9  747.93
#Mann= 3 , 0 , 0
       0     .06       0   284.6    .045       0   304.6     .06       0
Bank Sta=284.6,304.6
XS Rating Curve= 0 ,0
Exp/Cntr=0.3,0.1

Type RM Length L Ch R = 1 ,298.1   ,295.8,298.1,300.3
XS GIS Cut Line= 2
     1543644.963      422017.883     1544226.066      421794.781
#Sta/Elev= 30
      10   651.2    20.1  647.43    30.1   644.3    40.2     642    50.2  640.38
    60.2  639.47   100.4  636.85   230.9  628.79     261  626.68   281.2  624.92
   291.2  624.89   301.2  627.47   311.2  632.92   321.3  638.75   331.3  643.57
   361.4  656.13   391.5  668.06   401.6  671.78   411.6  674.97   431.7  680.71
   481.9  695.92   491.9  698.43     502  700.59   522.1  704.45   532.1   706.1
   542.1  707.44   552.2  708.44   592.3  711.99   612.4  714.35   622.5   715.9
#Mann= 3 , 0 , 0
       0     .06       0   281.2    .045       0   301.2     .06       0
Bank Sta=281.2,301.2
XS Rating Curve= 0 ,0
Exp/Cntr=0.3,0.1

Chan Stop Cuts=-1
Use User Specified Reach Order=0